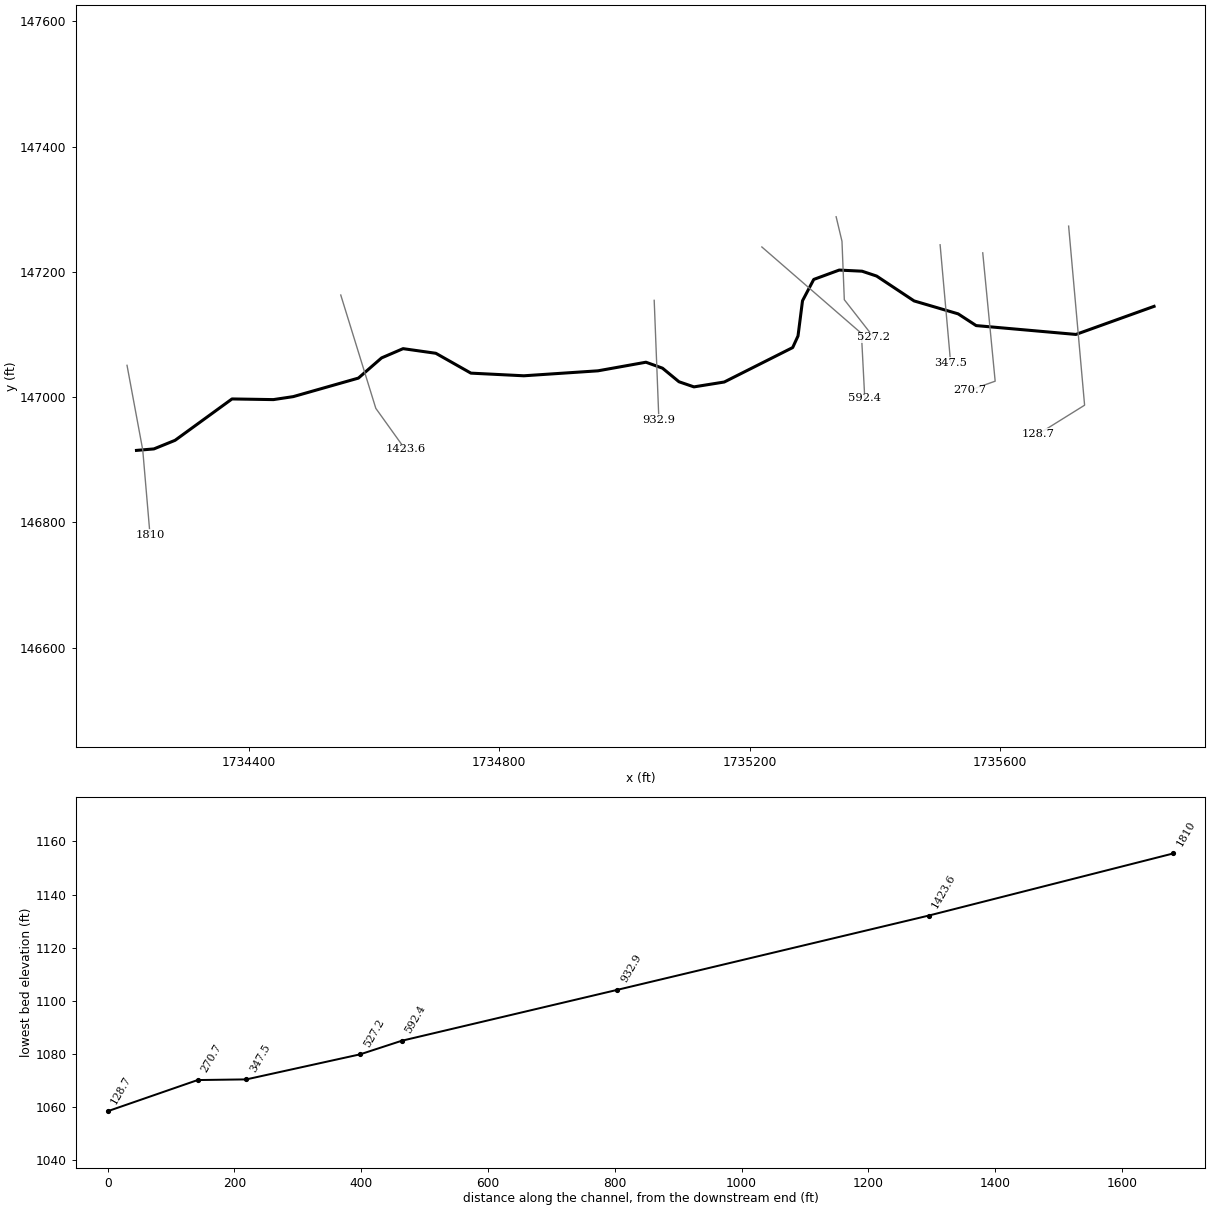
--- Grapevine Branch.prj (project) ---

Proj Title=Grapevine Branch
Current Plan=p01
Default Exp/Contr=0,0
English Units
Geom File=g01
Flow File=f01
Plan File=p01
BEGIN DESCRIPTION:
END DESCRIPTION:
DSS Export Rating Curves= 0
DSS Export Rating Curve Sorted= 0
DSS Export Volume Flow Curves= 0
DXF OffsetX= 0
DXF OffsetY= 0
DXF ScaleX= 0
DXF ScaleY= 0

--- Grapevine Branch.p01 (plan) ---

Plan Title=Floodplain
Program Version=4.00
Geom File=g01
Flow File=f01
K Sum by GR=0
Std Step Tol=0.01
Critical Tol=0.01
Num of Std Step Trials=20
Max Error Tol=0.3
Flow Tol Ratio=0.001
Split Flow NTrial=30
Split Flow Tol=0.02
Split Flow Ratio=0.02
Log Output Level=0
Friction Slope Method=1
Unsteady Friction Slope Method=2
Unsteady Bridges Friction Slope Method=1
Global Log Level=0
CheckData=False
Run HTab=0
Run UNet=0
Run PostProcess=0
UNET Theta=0
UNET Theta Warmup=0
UNET ZTol=0
UNET ZSATol=0
UNET MxIter=0
UNET MaxInSteps=0
UNET DtIC=0
UNET DtMin=0
UNET MaxCRTS=0
UNET WFStab=0
UNET SFStab=0
UNET WFX=0
UNET SFX=0
UNET DSS MLevel=0
UNET DZMax Abort=0
UNET Convert EG Bridges=0
UNET Use Existing IB Tables=0
UNET Froude Limit=0
UNET Froude Power=0
Write IC File=0
Echo Input=False
Echo Output=False
Write Detailed=0

--- Grapevine Branch.f01 (steady flow) ---

Flow Title=NFF Regression Equation
Program Version=4.00
Number of Profiles=1
Profile Names=P100yr
River Rch & RM=Grapevine Branch,Main      ,1810
568.2825
River Rch & RM=Grapevine Branch,Main      ,270.7
598.1698
Boundary for River Rch & Prof#=Grapevine Branch,Main      ,1
Up Type=0
Dn Type=3
Dn Slope=0.046228

--- Grapevine Branch.g01 (geometry) ---

Geom Title=Geometry
Program Version=4.00

River Reach=Grapevine Branch,Main
Reach XY= 30
     1734221.074      146915.089     1734248.896      146917.474
     1734282.707       146931.21     1734373.574      146997.247
     1734439.611      146996.191     1734471.309      147000.945
     1734575.384       147030.53     1734612.365      147062.756
     1734646.704      147077.548     1734699.006      147070.152
     1734755.005      147038.454     1734839.533      147034.228
     1734957.872      147042.152     1735034.475      147055.888
      1735060.89      147046.379     1735087.217      147024.698
     1735111.102      147016.509      1735159.52       147024.28
     1735268.756       147079.28     1735277.277      147097.803
      1735284.45      147153.992     1735302.383      147188.064
      1735343.03      147203.008     1735379.493      147201.215
     1735402.806      147193.444     1735462.603      147153.754
     1735532.928      147133.116     1735561.703      147114.378
     1735720.969      147100.247     1735845.756      147145.091

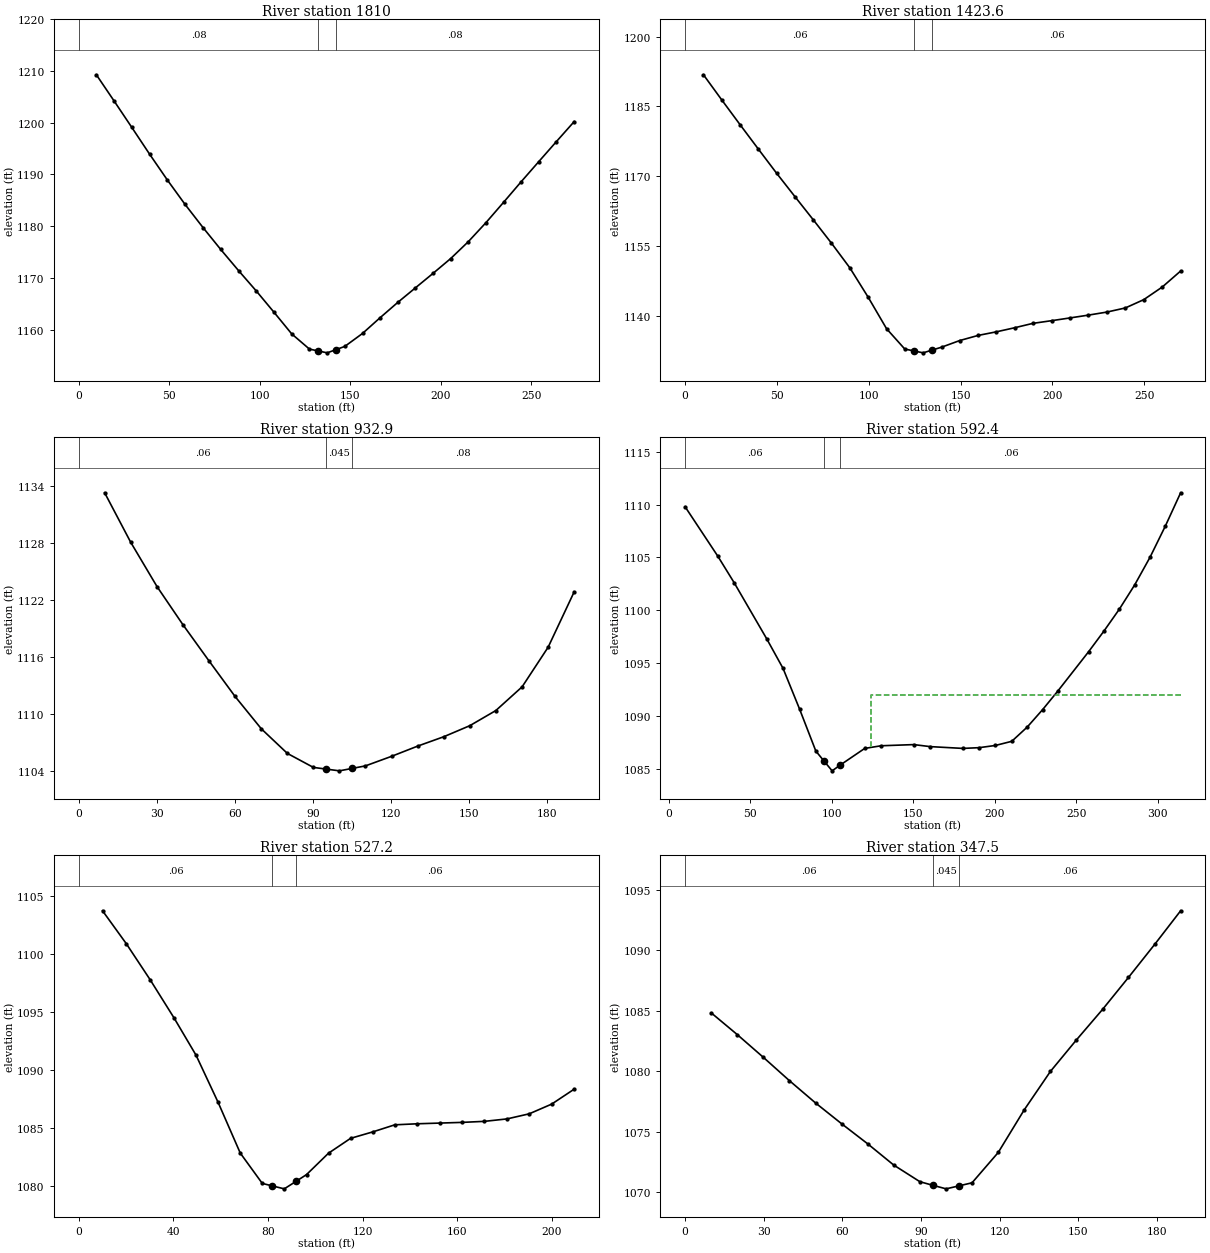
Type RM Length L Ch R = 1 ,1810    ,384.5,386.3,390.1
XS GIS Cut Line= 3
     1734205.952      147050.935     1734231.038      146915.943
     1734242.683      146780.083
#Sta/Elev= 30
     9.8 1209.26    19.6 1204.19    29.4 1199.07    39.2 1193.91      49 1188.92
    58.8 1184.19    68.7 1179.72    78.5 1175.48    88.3 1171.41    98.1 1167.47
   107.9 1163.35   117.7 1159.16   127.5 1156.22   132.3 1155.87   137.3  1155.5
   142.3 1156.14     147 1156.74   156.8 1159.25   166.5 1162.29   176.3 1165.26
     186 1168.06   195.7 1170.85   205.5 1173.73   215.2 1176.98     225 1180.68
   234.7  1184.6   244.4 1188.57   254.2 1192.49   263.9 1196.35   273.7 1200.21
#Mann= 3 , 0 , 0
       0     .08       0   132.3    .045       0   142.3     .08       0
Bank Sta=132.3,142.3
XS Rating Curve= 0 ,0
Exp/Cntr=0.3,0.1

Type RM Length L Ch R = 1 ,1423.6  ,495.4,490.8,486.6
XS GIS Cut Line= 3
     1734547.228      147163.164     1734603.189      146982.224
     1734650.047      146916.849
#Sta/Elev= 29
      10 1191.81    19.9 1186.44    29.9  1181.1    39.9 1175.83    49.8 1170.66
    59.8 1165.62    69.8 1160.63    79.7 1155.61    89.7 1150.31    99.7 1143.98
   109.7 1137.22   119.6 1132.86   124.6 1132.45   129.6 1132.04   134.6 1132.65
   139.6 1133.25   149.5 1134.68   159.5 1135.78   169.5 1136.56   179.4 1137.43
   189.4 1138.38   199.5 1138.95   209.5 1139.54   219.6 1140.15   229.6  1140.8
   239.7 1141.69   249.7 1143.47   259.8 1146.19   269.8 1149.63
#Mann= 3 , 0 , 0
       0     .06       0   124.6    .045       0   134.6     .06       0
Bank Sta=124.6,134.6
XS Rating Curve= 0 ,0
Exp/Cntr=0.3,0.1

Type RM Length L Ch R = 1 ,932.9   ,323.9,340.5,356.6
XS GIS Cut Line= 2
     1735047.663      147154.683     1735055.125      146964.417
#Sta/Elev= 21
      10 1133.25      20 1128.06    30.1 1123.41    40.1 1119.39    50.1  1115.6
    60.1 1111.87    70.2 1108.47    80.2 1105.89    90.2 1104.42    95.2 1104.24
   100.2 1104.06   105.2 1104.32   110.2 1104.58   120.3 1105.59   130.3 1106.66
   140.3 1107.64   150.3  1108.8   160.3 1110.39   170.4 1112.88   180.4 1117.04
   190.4 1122.85
#Mann= 3 , 0 , 0
       0     .06       0    95.2    .045       0   105.2     .08       0
Bank Sta=95.2,105.2
XS Rating Curve= 0 ,0
Exp/Cntr=0.3,0.1

Type RM Length L Ch R = 1 ,592.4   ,82.2,65.2,48.1
XS GIS Cut Line= 3
     1735219.546      147239.888     1735378.479      147101.964
     1735383.833      146998.497
#Sta/Elev= 28
      10 1109.79    30.1 1105.11    40.1 1102.61    60.1  1097.3    70.1 1094.51
    80.2 1090.68    90.2  1086.7    95.2 1085.76   100.2 1084.83   105.2 1085.38
   120.2 1086.95   130.3  1087.2   150.3 1087.31   160.3 1087.12   180.4 1086.95
   190.4 1087.02   200.4 1087.23   210.4 1087.62   219.9 1088.97   229.3 1090.61
   238.7 1092.38   257.5 1096.08   266.9 1098.03   276.4 1100.11   285.8  1102.4
   295.2 1105.01   304.6 1107.96     314 1111.11
#Mann= 3 , 0 , 0
      10     .06       0    95.2    .045       0   105.2     .06       0
#XS Ineff= 2 , 0
                          123.91         1092.01
Permanent Ineff=
       F       F
Bank Sta=95.2,105.2
XS Rating Curve= 0 ,0
Exp/Cntr=0.3,0.1

Type RM Length L Ch R = 1 ,527.2   ,178.5,179.7,180.9
XS GIS Cut Line= 4
     1735338.142      147288.143     1735347.468      147248.971
     1735351.199      147155.703     1735397.833      147096.011
#Sta/Elev= 24
    10.1 1103.76    20.1 1100.93    30.2 1097.81    40.3 1094.51    49.6 1091.29
    58.9 1087.23    68.3 1082.83    77.6 1080.21    81.9 1079.99    86.9 1079.74
    91.9 1080.39    96.3 1080.97   105.6 1082.82   114.9  1084.1   124.3 1084.66
   133.6 1085.27   143.1 1085.36   152.5 1085.42     162 1085.48   171.5 1085.57
     181 1085.78   190.4 1086.22   199.9 1087.06   209.4 1088.35
#Mann= 3 , 0 , 0
       0     .06       0    81.9    .045       0    91.9     .06       0
Bank Sta=81.9,91.9
XS Rating Curve= 0 ,0
Exp/Cntr=0.3,0.1

Type RM Length L Ch R = 1 ,347.5   ,76.7,76.8,76.7
XS GIS Cut Line= 2
     1735504.159      147243.375     1735520.947      147054.973
#Sta/Elev= 21
      10 1084.83    19.9 1083.04    29.9 1081.15    39.8 1079.23    49.8 1077.38
    59.7 1075.67    69.7    1074    79.6 1072.25    89.6 1070.87    94.6 1070.57
    99.6 1070.28   104.6 1070.53   109.5 1070.78   119.5 1073.29   129.4 1076.81
   139.4 1079.99   149.3 1082.59   159.3 1085.12   169.2 1087.77   179.2  1090.5
   189.1 1093.28
#Mann= 3 , 0 , 0
       0     .06       0    94.6    .045       0   104.6     .06       0
Bank Sta=94.6,104.6
XS Rating Curve= 0 ,0
Exp/Cntr=0.3,0.1

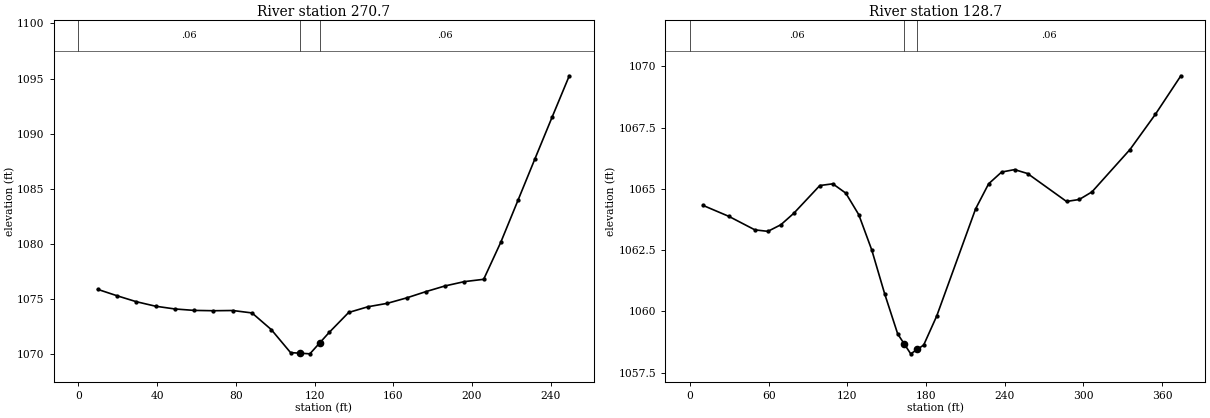
Type RM Length L Ch R = 1 ,270.7   ,142.2,142,141.8
XS GIS Cut Line= 3
     1735572.229      147230.522     1735592.061        147025.6
     1735551.076      147011.057
#Sta/Elev= 28
     9.8 1075.88    19.6  1075.3    29.4 1074.76    39.2 1074.35      49  1074.1
    58.8 1073.97    68.6 1073.94    78.4 1073.96    88.2 1073.74      98 1072.23
   107.8 1070.14   112.6 1070.09   117.6 1070.03   122.6 1071.02   127.4 1071.97
   137.3 1073.78   147.1  1074.3   156.9 1074.61   166.7  1075.1   176.5 1075.67
   186.3 1076.19   196.1 1076.58   205.9 1076.79   214.6 1080.15   223.3 1083.94
     232 1087.74   240.7 1091.51   249.4 1095.25
#Mann= 3 , 0 , 0
       0     .06       0   112.6    .045       0   122.6     .06       0
Bank Sta=112.6,122.6
XS Rating Curve= 0 ,0
Exp/Cntr=0.3,0.1

Type RM Length L Ch R = 1 ,128.7   ,123.2,128.7,134.2
XS GIS Cut Line= 3
     1735709.348       147273.22     1735734.845       146987.26
     1735660.849      146941.186
#Sta/Elev= 29
     9.9 1064.33    29.7 1063.88    49.5 1063.33    59.4 1063.27    69.3 1063.54
    79.2 1064.01      99 1065.14   108.9 1065.21   118.8 1064.83   128.7 1063.95
   138.6 1062.51   148.5 1060.71   158.4 1059.08   163.3 1058.68   168.3 1058.27
   173.3 1058.45   178.2 1058.63   188.1 1059.81   217.8 1064.19   227.7 1065.21
   237.6 1065.69   247.5 1065.79   257.4 1065.63   287.1 1064.49   296.8 1064.57
   306.5 1064.88   335.5 1066.61   354.9 1068.05   374.3 1069.62
#Mann= 3 , 0 , 0
       0     .06       0   163.3    .045       0   173.3     .06       0
Bank Sta=163.3,173.3
XS Rating Curve= 0 ,0
Exp/Cntr=0.3,0.1

Chan Stop Cuts=-1
Use User Specified Reach Order=0